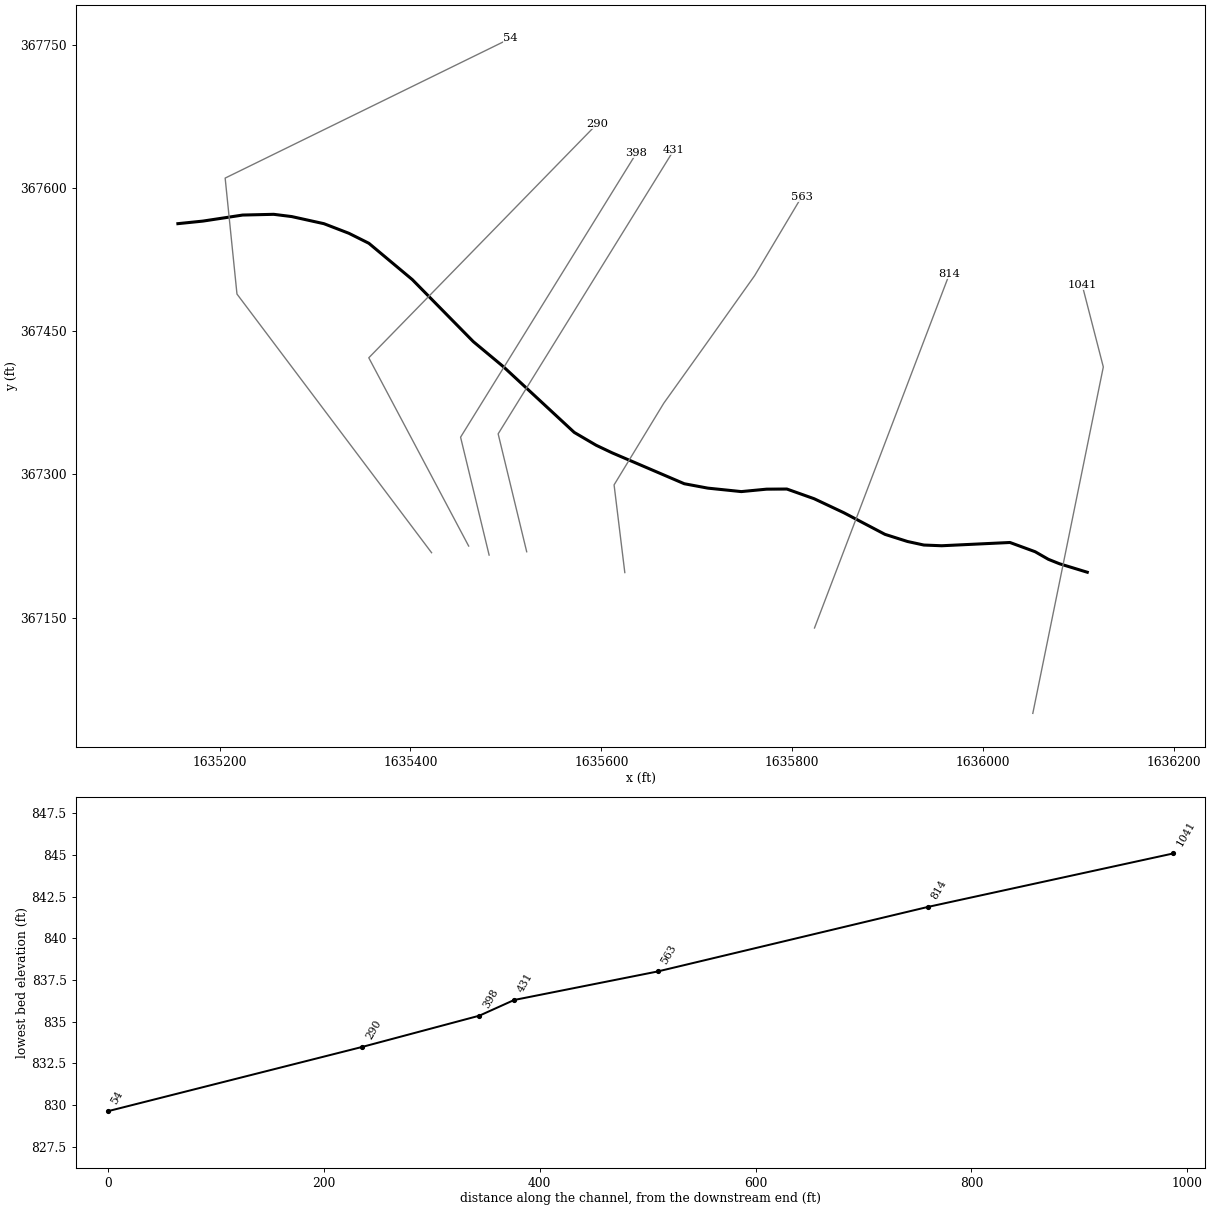
--- PINEYFKT1.prj (project) ---

Proj Title=PINEYFKT1
Current Plan=p01
Default Exp/Contr=0,0
English Units
Geom File=g01
Flow File=f01
Plan File=p01
BEGIN DESCRIPTION:
---------- MODELED AS PART OF WVEMD CTP PROGRAM, 2023----------
Stream Name: Piney Fork Tributary 1
Flood Zone:  AFH
Wetzel County, WV
HEC-RAS Version: RAS 6.3
Vertical Datum: NAVD88
Projection: NAD 1983 StatePlane West Virginia S FIPS 4702 (US Feet)
Terrain: 1-meter West Virginia FEMA R3 South Central (collected 2018-2020)
Land Use: 2019 NLCD
Hydrologic Method:
WV 2010 Regional Regression Equations
Additional Model Notes:
None
END DESCRIPTION:
DSS Export Rating Curves= 0
DSS Export Rating Curve Sorted= 0
DSS Export Volume Flow Curves= 0
DXF OffsetX= 0
DXF OffsetY= 0
DXF ScaleX= 0
DXF ScaleY= 0

--- PINEYFKT1.p01 (plan) ---

Plan Title=Floodplain
Program Version=6.30
Short Identifier=Floodplain
Geom File=g01
Flow File=f01
Subcritical Flow
K Sum by GR= 0
Std Step Tol= 0.01
Critical Tol= 0.01
Num of Std Step Trials= 20
Max Error Tol= 0.3
Flow Tol Ratio= 0.001
Split Flow NTrial= 30
Split Flow Tol= 0.02
Split Flow Ratio= 0.02
Log Output Level= 0
Friction Slope Method= 1
Unsteady Friction Slope Method= 2
Unsteady Bridges Friction Slope Method= 1
Parabolic Critical Depth
Global Vel Dist= 0 , 0 , 0
Global Log Level= 0
CheckData=True
Encroach Param=-1 ,0,0, 0
Mapping Interval=1HOUR
Computation Time Step Use Courant=        0
Computation Time Step Use Time Series=    0
Computation Time Step Count To Double=0
Computation Time Step Max Doubling=0
Computation Time Step Max Halving=0
Computation Time Step Residence Courant=0
Run HTab= 0
Run UNet= 0
Run Sediment= 0
Run PostProcess= 0
Run WQNet= 0
Run RASMapper= 0
UNET Theta= 0
UNET Theta Warmup= 0
UNET ZTol= 0
UNET ZSATol= 0
UNET MxIter= 0
UNET Max Iter WO Improvement= 0
UNET MaxInSteps= 0
UNET DtIC= 0
UNET DtMin= 0
UNET MaxCRTS= 0
UNET WFStab= 0
UNET SFStab= 0
UNET WFX= 1
UNET SFX= 1
UNET Gravity=32.17405
UNET 1D Methodology=Finite Difference
UNET DSS MLevel= 1
UNET Pardiso=0
UNET DZMax Abort= 0
UNET Use Existing IB Tables= 0
UNET Froude Reduction=False
UNET Froude Limit= 0
UNET Froude Power= 0
UNET D1 Cores= 0
UNET WindReference=Eulerian
UNET WindDragFormulation=Hsu (1988)
UNET D2 Coriolis=0
UNET D2 Cores= 0
UNET D2 Theta= 1
UNET D2 Theta Warmup= 1
UNET D2 Z Tol= 0.01
UNET D2 Volume Tol= 0.01
UNET D2 Max Iterations= 20
UNET D2 Equation= 0
UNET D2 RampUpFraction=0.1
UNET D2 TimeSlices= 1
UNET D2 Turbulence Formulation=Non-Conservative (original)
UNET D2 Eddy Viscosity=0.3
UNET D2 Transverse Eddy Viscosity=0.1
UNET D2 Smagorinsky Mixing=0
UNET D2 BCVolumeCheck=0
UNET D2 Cores=0
UNET D2 SolverType=PARDISO (Direct)
UNET D2 Minimum Iterations= 3
UNET D2 Maximum Iterations= 30
UNET D2 Restart Number= 10
UNET D2 Relaxation Coeff=1.3
UNET D2 SOR Precondition Iterations= 10
UNET D2 ILUT Maximum Fill= 8
UNET D2 ILUT Tolerance=1E-08
UNET D2 Convergence Tolerance=0.00001
UNET D1D2 MaxIter= 0
UNET D1D2 ZTol=0.01
UNET D1D2 QTol=0.1
UNET D1D2 MinQTol=1
Write IC File= 0
Write IC File at Fixed DateTime=0
Write IC File at Sim End=0
Echo Input=False
Echo Parameters=False
Echo Output=False
Write Detailed= 0
HDF Write Warmup=0
HDF Write Time Slices=0
HDF Flush=0
HDF Compression= 1
HDF Chunk Size= 1
HDF Spatial Parts= 1
HDF Use Max Rows=0
HDF Fixed Rows= 1
Calibration Method= 0
Calibration Iterations= 20
Calibration Max Change=0.05
Calibration Tolerance=0.2
Calibration Maximum=1.5
Calibration Minimum=0.5
Calibration Optimization Method= 1
WQ AD Non Conservative
WQ ULTIMATE=-1
WQ Max Comp Step=1HOUR
WQ Output Interval=15MIN
WQ Output Selected Increments= 0
WQ Output face flow=0
WQ Output face velocity=0
WQ Output face area=0
WQ Output face dispersion=0
WQ Output cell volume=0
WQ Output cell surface area=0
WQ Output cell continuity=0
WQ Output cumulative cell continuity=0
WQ Output face conc=0
WQ Output face dconc_dx=0
WQ Output face courant=0
WQ Output face peclet=0
WQ Output face adv mass=0
WQ Output face disp mass=0
WQ Output cell mass=0
WQ Output cell source sink temp=0
WQ Output nsm pathways=0
WQ Output nsm derived pathways=0
WQ Create Restart=0
WQ Fixed Restart=0
WQ System Summary=0
WQ Write To DSS=0
Sorting and Armoring Iterations= 10
XS Update Threshold= 0.02
Bed Roughness Predictor= 0
Hydraulics Update Threshold= 0.02
Energy Slope Method= 1
Volume Change Method= 1
Sediment Retention Method= 0
Sediment TS Multiplier= 1
Warm Up Method= 0
XS Weighting Method= 0
Number of US Weighted Cross Sections= 1
Number of DS Weighted Cross Sections= 1
Upstream XS Weight=0
Main XS Weight=1
Downstream XS Weight=0
Number of DS XS's Weighted with US Boundary= 1
Upstream Boundary Weight= 1
Weight of XSs Associated with US Boundary= 0
Number of US XS's Weighted with DS Boundary= 1
Downstream Boundary Weight= 0.5
Weight of XSs Associated with DS Boundary= 0.5
Percentile Method= 0
Sediment Output Level= 3
Mass or Volume Output= 0
Output Increment Type= 1
Profile and TS Output Increment= 1
Transport Output Increment 1
XS Output Flag= 0
XS Output Increment= 10
Read HDF5 Sediment Hotstart= 0
Sediment Hotstart Type= 0
Write Gradation File= 0
Read Gradation Hotstart= 0
Write HDF5 File= 1
Write Binary Output= 1
Write DSS Sediment File= 0
DSS Sediment Output Type= 1
SV Curve= 0
Specific Gage Flag= 0
Subcell Erosion Methods= 0
Subcell Deposition Methods= 0
Advection Scheme= 1
Matrix Solver= 0
Implicit Weighting Factor= 1
Maximum Outer Loop Convergence Iterations= 5
Convergence Maximum Absolute= 0.001
Convergence RMSE= 0.0001
Grain Fractions Max Abs Error= 0.001
Max Subgrid Regions= 1
Max Subgrid Length Scale= 3.402823E+38
Initial Layer Thickness= 3.402823E+38
Min Layer Thickness= 3.402823E+38
Max Layer Thickness= 3.402823E+38
Number of Layers= 5

--- PINEYFKT1.f01 (steady flow) ---

Flow Title=Flow
Program Version=6.30
Number of Profiles= 1
Profile Names=F01pct
River Rch & RM=PINEYFKT1,Main            ,1041
     582
Boundary for River Rch & Prof#=PINEYFKT1,Main            , 1
Up Type= 0
Dn Type= 3
Dn Slope=0.01663
DSS Import GetInterval= 0
DSS Import GetPeak= 0
DSS Import FillOption= 0

--- PINEYFKT1.g01 (geometry) ---

Geom Title=Geometry
Program Version=6.30

River Reach=PINEYFKT1       ,Main
Reach XY= 30
1636109.13135666367197.5162837591636080.08346798367206.380529737
1636068.33640525 367211.079354831636054.53360653367219.008622174
1636028.10271539367228.699948928     1635956.546      367225.286
     1635937.873      367226.033     1635920.695      367229.767
     1635897.167      367237.2361635854.10113666367259.878219797
1635822.97194258 367274.563162381635794.37714653367284.739015849
1635773.16616238367284.600235646     1635746.668       367282.05
1635711.48339803367285.692146531     1635686.916 367290.28283762
1635611.19326734367322.7269108851635594.58035684367330.615055259
1635571.61285347367344.087926734     1635497.205       367413.13
     1635465.835      367439.271     1635401.976      367504.251
     1635356.415      367542.343     1635335.502      367552.799
     1635309.361 367562.865162381635275.54386932 367570.33416238
1635256.74534061367572.6838534691635224.18032476367571.920015849
1635182.60638218367565.588853469     1635156.354      367562.891

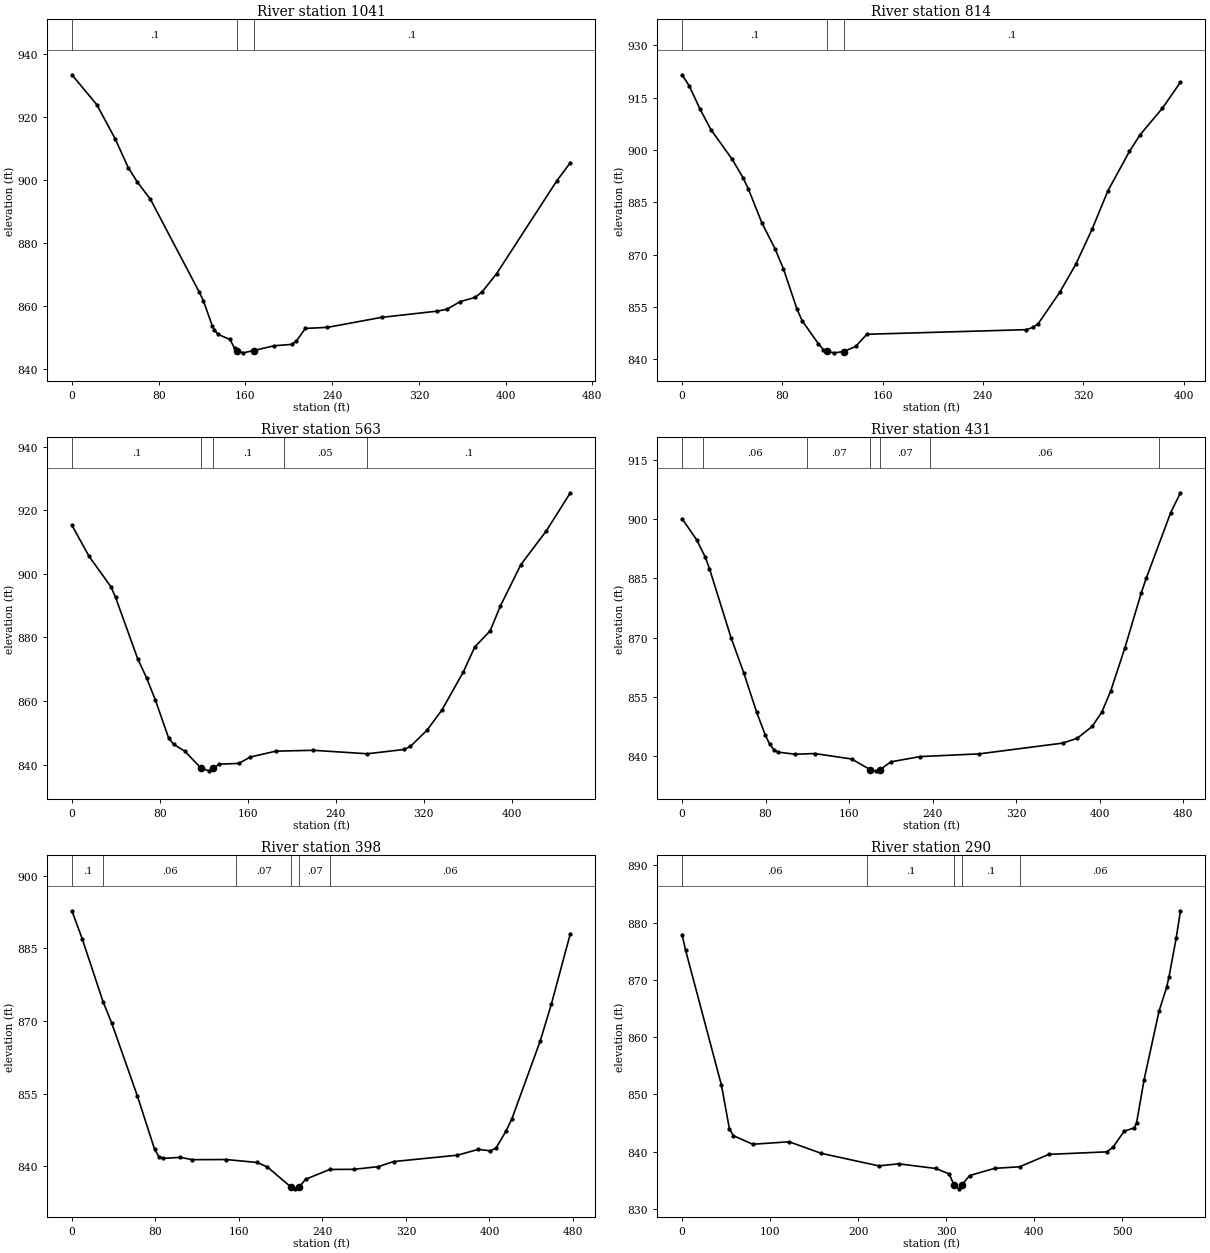
Type RM Length L Ch R = 1 ,1041    ,228.4,227.5,226.3
XS GIS Cut Line= 3
1636052.05814342367049.5806191441636125.92567694367412.700987607
1636103.66074207367499.049946772
#Sta/Elev= 30
       0  933.26    22.9  923.81    39.8  913.02      52   903.8    60.2  899.32
    72.4   893.8   117.3  864.45   121.3  861.57   129.6  853.49   131.4  852.38
   134.8  850.93   145.9  849.32     150  846.52   152.3  845.79   158.1  845.09
   167.7  845.83   186.7  847.34     203  847.78   207.1  848.88   215.3  852.83
   235.7  853.17   285.6  856.34   336.8  858.31   345.9  858.91   358.1  861.34
   371.9  862.66   378.5   864.5   391.6  870.16   447.4  899.73   459.7  905.39
#Mann= 3 ,-1,0
       0      .1       0   152.3    .045       0   167.7      .1       0
Bank Sta=152.3,167.7
XS Rating Curve= 0 ,0
Exp/Cntr(USF)=0,0
Exp/Cntr=0.3,0.1

Type RM Length L Ch R = 1 ,814     ,250.9,250.3,249.4
XS GIS Cut Line= 2
1635823.32723035367139.0845345511635964.82626729367510.519506518
#Sta/Elev= 30
       0  921.56     5.8  918.34    14.4  911.69      23  905.85    40.1  897.29
    48.6  892.08    52.9  888.85    63.7   879.1    74.3   871.6    80.9  865.91
    91.6  854.49    95.7  851.12   108.6  844.55   112.8  842.75   115.3842.2787
   121.4  841.88   128.8  842.24   138.5  843.73   147.4   847.2   274.5  848.52
   279.8  849.16   284.1  850.26   301.2  859.23     314  867.26   326.9  877.24
   339.7  888.37   356.8  899.61   365.4  904.43     383  911.94   397.5  919.45
#Mann= 3 ,-1,0
       0      .1       0   115.3    .045       0   128.8      .1       0
Bank Sta=115.3,128.8
XS Rating Curve= 0 ,0
Exp/Cntr(USF)=0,0
Exp/Cntr=0.3,0.1

Type RM Length L Ch R = 1 ,563     ,133,132.9,132.9
XS GIS Cut Line= 6
1635624.59384593367197.1628637321635613.35635323367289.085221367
1635665.38708906 367374.640496451635709.32138439367436.158089953
1635760.61262039367508.3856357951635810.00589431367591.255220698
#Sta/Elev= 30
       0  915.27    15.5  905.54    35.6  895.86    39.7  892.59    59.8   873.3
    67.9  867.28    75.9  860.31      88  848.32    92.6  846.35   102.9  844.13
   117.5  838.83   124.7  838.01   128.3838.8609   134.1  840.11   151.8  840.34
   162.2  842.35   185.6  844.21   219.6  844.47   268.8  843.38   302.2  844.73
   307.9  845.69   322.8   850.7   336.6  857.15   356.1  869.16   366.4  876.95
   380.4  882.03   389.7  889.81   408.3  902.83   431.6  913.52   453.4  925.47
#Mann= 5 ,-1,0
       0      .1       0   117.5    .045       0   128.3      .1       0
  192.61     .05       0  268.34      .1       0
Bank Sta=117.5,128.3
XS Rating Curve= 0 ,0
Exp/Cntr(USF)=0,0
Exp/Cntr=0.3,0.1

Type RM Length L Ch R = 1 ,431     ,32.2,32.2,31.9
XS GIS Cut Line= 3
1635521.78985563367218.9987400041635491.89254019367342.574310514
1635676.25931877367640.550887791
#Sta/Elev= 30
       0  900.15    13.9  894.84    22.2  890.44    26.3  887.48    46.9  870.05
    59.2  861.06    71.5  851.13    79.8  845.32    83.9  843.09      88  841.63
    92.1  841.03   108.6   840.5   127.1  840.68   162.4   839.3  180.28836.6072
   185.9   836.3   189.8  836.61     200  838.58   228.2  839.91   284.7   840.6
   364.6  843.32   378.6  844.55   392.9  847.54   402.3  851.25   410.6  856.48
   424.1  867.33   439.9  881.33   444.6     885   468.1  901.66   477.5   906.7
#Mann= 7 ,-1,0
       0      .1       0      20     .06       0     120     .07       0
  180.28    .045       0   189.8     .07       0  237.14     .06       0
  457.14      .1       0
Bank Sta=180.28,189.8
XS Rating Curve= 0 ,0
Exp/Cntr(USF)=0,0
Exp/Cntr=0.3,0.1

Type RM Length L Ch R = 1 ,398     ,109.1,108.3,107.4
XS GIS Cut Line= 3
1635482.42505696367215.5107198691635452.52774152367339.086290378
 1635636.8945201367637.062867656
#Sta/Elev= 30
       0  892.77     9.8  887.03    29.9  873.96    38.1  869.61    62.8  854.49
    79.2  843.54    83.4  841.99    87.5  841.65   103.9  841.86   115.4  841.38
   147.7  841.41   177.3  840.81   187.2  839.89     210   835.7   213.5  835.36
   217.6   835.7   223.8  837.33     247  839.36     270  839.39   293.5  839.94
   308.1  840.99   369.1   842.3   389.4  843.51     401   843.2   406.4  843.82
   415.8  847.26   421.4  849.76   448.7  865.93   459.2  873.42   477.5  888.06
#Mann= 6 ,-1,0
       0      .1       0      30     .06       0  157.14     .07       0
     210    .045       0   217.6     .07       0  247.14     .06       0
Bank Sta=210,217.6
XS Rating Curve= 0 ,0
Exp/Cntr(USF)=0,0
Exp/Cntr=0.3,0.1

Type RM Length L Ch R = 1 ,290     ,231.3,235.9,240.8
XS GIS Cut Line= 3
1635460.99864756367224.978203093 1635356.3580435367422.300485036
1635595.53656707367667.458471692
#Sta/Elev= 30
       0   877.9       4  875.19    44.8  851.56    53.8  843.95    58.4  842.77
    80.2  841.28   121.6  841.71     158  839.69   223.4   837.5   245.9  837.86
   287.9  837.05   303.2  836.11   308.9  834.13   314.7  833.49  317.65 834.197
   326.6  835.82     355  837.07   383.2  837.34   416.5  839.51   482.2  839.95
   489.1  840.73     502  843.56   513.3  844.13   516.1  845.07   524.6  852.57
   541.6  864.57   550.1  868.66   552.9  870.55     561  877.29   565.9  882.06
#Mann= 5 ,-1,0
       0     .06       0     210      .1       0   308.9    .045       0
  317.65      .1       0  383.35     .06       0
Bank Sta=308.9,317.65
XS Rating Curve= 0 ,0
Exp/Cntr(USF)=0,0
Exp/Cntr=0.3,0.1

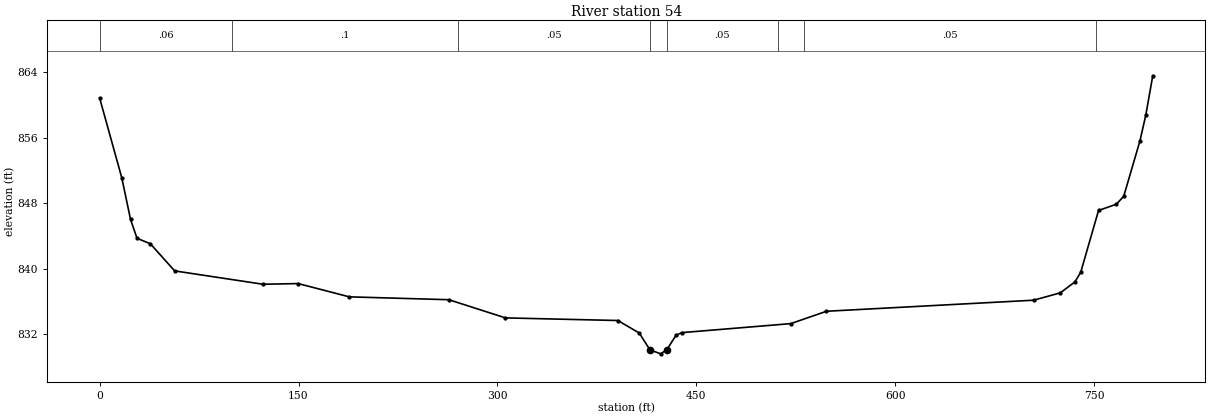
Type RM Length L Ch R = 1 ,54      ,,,
XS GIS Cut Line= 4
1635422.13213748367218.0021628221635218.25772202367489.110212471
1635205.87488909367610.6535723451635504.84804355 367757.15041803
#Sta/Elev= 30
       0  860.87    16.7  851.13    23.3  846.05    28.2  843.74    38.2  843.08
    56.6  839.76   123.2  838.13   149.8  838.21   188.3  836.59   263.4  836.24
   306.1  834.02   390.9   833.7     407  832.17     415  830.13   423.1  829.63
  427.75 830.125   434.7  831.89   439.1  832.22   521.3  833.32   548.2  834.83
   704.4  836.18   724.6  837.08   735.6  838.42     740  839.61   753.4  847.14
   766.8   847.9   772.4  848.87   784.6  855.62     789  858.75   794.3  863.59
#Mann= 8 ,-1,0
       0     .06       0     100      .1       0     270     .05       0
     415    .045       0  427.75     .05       0  511.38      .1       0
  531.38     .05       0  751.38     .06       0
Bank Sta=415,427.75
XS Rating Curve= 0 ,0
Exp/Cntr(USF)=0,0
Exp/Cntr=0.3,0.1
LCMann Table=0

Chan Stop Cuts=-1
Use User Specified Reach Order=0
Composite Channel Slope=5